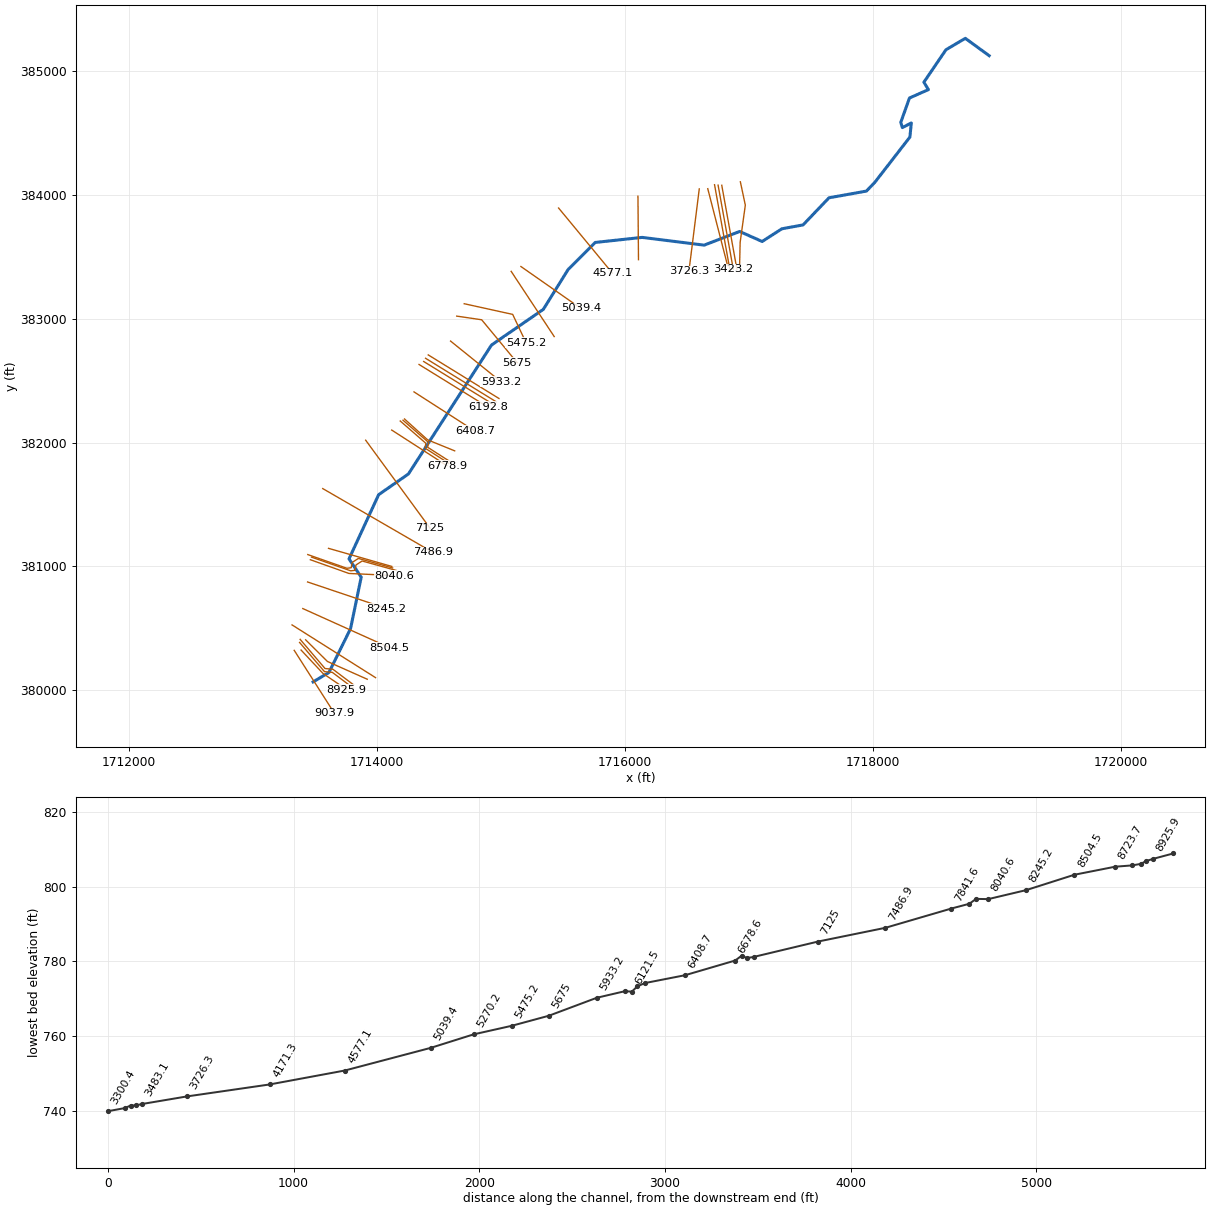
--- MUDFK.prj (project) ---

Proj Title=MUDFK
Current Plan=p01
Default Exp/Contr=0,0
English Units
Geom File=g01
Flow File=f01
Plan File=p01
BEGIN DESCRIPTION:
END DESCRIPTION:
DSS Export Rating Curves= 0
DSS Export Rating Curve Sorted= 0
DSS Export Volume Flow Curves= 0
DXF OffsetX= 0
DXF OffsetY= 0
DXF ScaleX= 0
DXF ScaleY= 0

--- MUDFK.p01 (plan) ---

Plan Title=Floodplain
Program Version=4.00
Geom File=g01
Flow File=f01
K Sum by GR=0
Std Step Tol=0.01
Critical Tol=0.01
Num of Std Step Trials=20
Max Error Tol=0.3
Flow Tol Ratio=0.001
Split Flow NTrial=30
Split Flow Tol=0.02
Split Flow Ratio=0.02
Log Output Level=0
Friction Slope Method=1
Unsteady Friction Slope Method=2
Unsteady Bridges Friction Slope Method=1
Global Log Level=0
CheckData=False
Run HTab=0
Run UNet=0
Run PostProcess=0
UNET Theta=0
UNET Theta Warmup=0
UNET ZTol=0
UNET ZSATol=0
UNET MxIter=0
UNET MaxInSteps=0
UNET DtIC=0
UNET DtMin=0
UNET MaxCRTS=0
UNET WFStab=0
UNET SFStab=0
UNET WFX=0
UNET SFX=0
UNET DSS MLevel=0
UNET DZMax Abort=0
UNET Convert EG Bridges=0
UNET Use Existing IB Tables=0
UNET Froude Limit=0
UNET Froude Power=0
Write IC File=0
Echo Input=False
Echo Output=False
Write Detailed=0

--- MUDFK.f01 (steady flow) ---

Flow Title=NFF Regression Equation
Program Version=4.00
Number of Profiles=1
Profile Names=P100yr
River Rch & RM=MUDFK,Main      ,9037.9
883.5589
River Rch & RM=MUDFK,Main      ,5675
990.5840
River Rch & RM=MUDFK,Main      ,2384.8
1302.880
River Rch & RM=MUDFK,Main      ,169.2
1329.090
Boundary for River Rch & Prof#=MUDFK,Main      ,1
Up Type=0
Dn Type=3
Dn Slope=0.004195

--- MUDFK.g01 (geometry) ---

Geom Title=USGS 10m DEM
Program Version=4.10

River Reach=MUDFK           ,Main
Reach XY= 30
     1713485.782      380068.685     1713613.355      380144.973
     1713787.854       380498.33     1713873.785      380913.831
     1713775.694      381061.401      1714014.41      381579.283
     1714254.861      381746.384        1714925.      382786.487
     1715342.535      383073.814     1715543.924      383396.904
     1715761.806      383613.918     1716140.278      383654.717
     1716640.278      383592.217     1716926.736       383702.46
      1717108.16      383621.731     1717267.014      383724.074
     1717438.021      383755.324     1717647.222      383974.075
     1717949.306      384028.328     1718016.146      384097.773
        1718300.      384464.005     1718311.285       384577.72
     1718239.236      384540.394     1718226.215      384582.061
     1718296.528      384779.109     1718449.305      384846.817
     1718412.848      384906.713     1718590.799      385168.432
     1718747.049      385260.446     1718939.219      385120.581

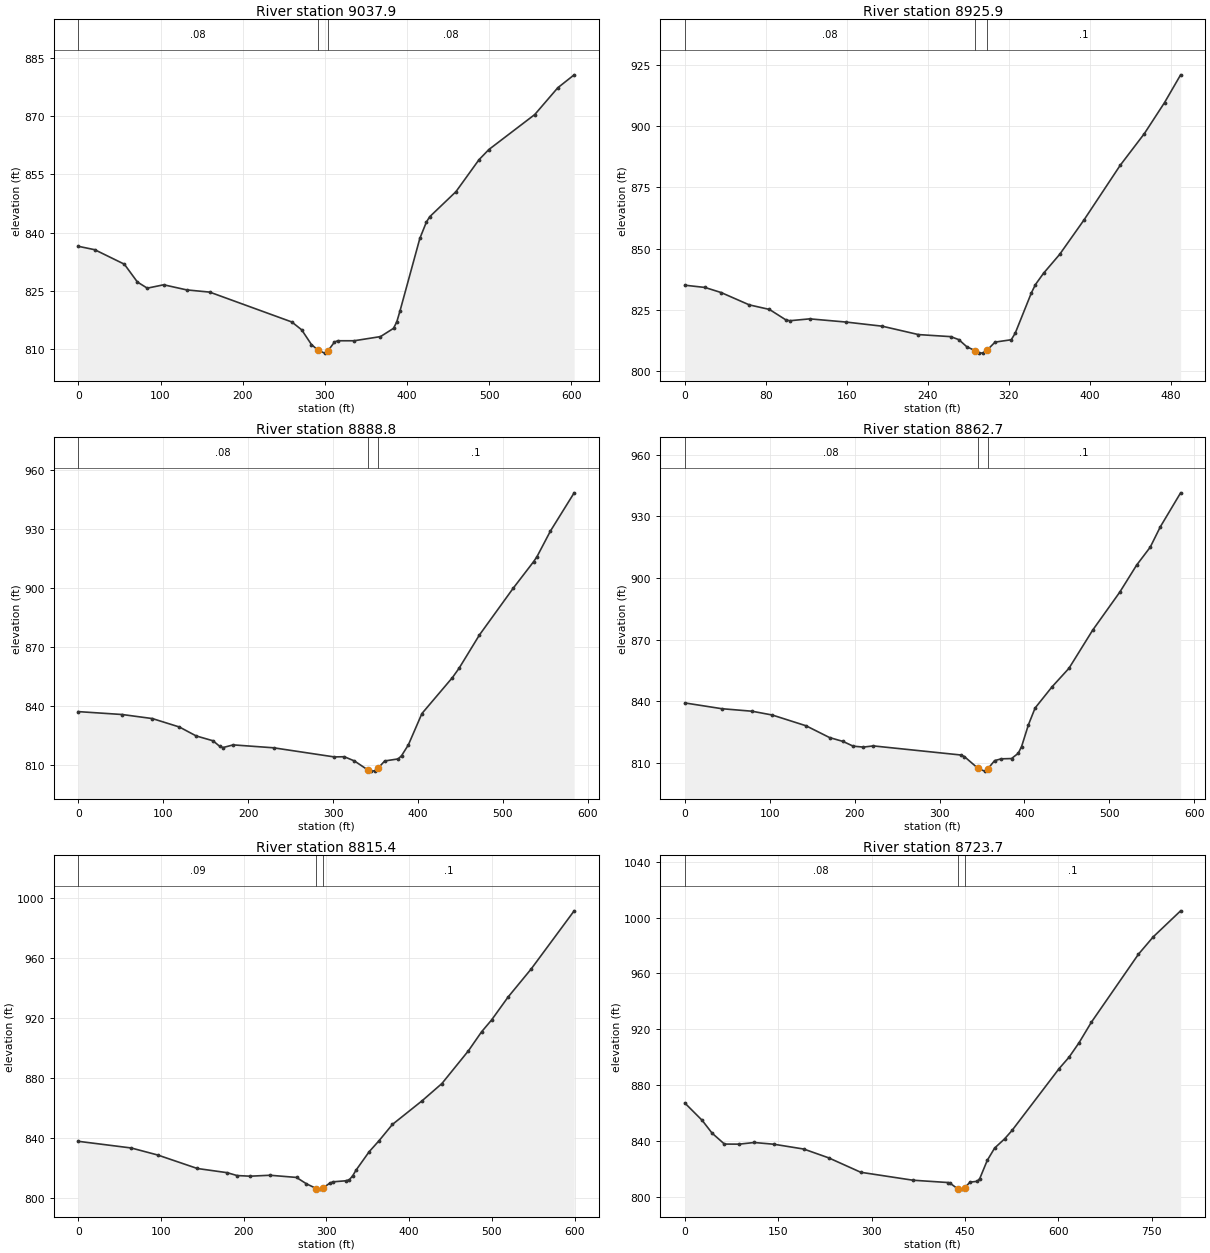
Type RM Length L Ch R = 1 ,9037.9  ,101.4,112,121.9
XS GIS Cut Line= 2
     1713333.401       380323.87     1713658.053      379815.189
#Sta/Elev= 30
       0  836.45      20  835.57      56  831.84    71.9  827.24    83.9  825.66
   103.9  826.53   131.9  825.21   159.9  824.64   259.8  816.94   271.8  814.92
   283.7  811.12   291.7  809.69   299.7  808.91   303.7  809.47   311.7  811.76
   315.7   812.1   335.7   812.1   367.7  813.17   383.6   815.3   387.6  817.01
   391.6   819.9   415.6  838.48   423.6  842.71   427.6  844.07   459.6  850.55
   487.6  858.78   499.6   861.4   555.5  870.43   583.5  877.33   603.4  880.66
#Mann= 3 , 0 , 0
       0     .08       0   291.7    .045       0   303.7     .08       0
Bank Sta=291.7,303.7
XS Rating Curve= 0 ,0
Exp/Cntr=0.3,0.1

Type RM Length L Ch R = 1 ,8925.9  ,23.1,37,50
XS GIS Cut Line= 3
     1713388.812      380325.973     1713565.678      380137.171
      1713756.65      380006.963
#Sta/Elev= 30
       0  835.11    19.9  834.19    35.8  832.13    63.7  827.09    83.6  825.23
    99.5  821.06   103.5  820.62   123.4  821.39   159.2  820.09     195   818.4
   230.8  814.98   262.7  814.14   270.7  812.92   278.6  810.01   286.6  808.47
   290.6  807.42   294.6   807.5   298.6  808.64   306.5  811.91   322.5  812.88
   326.4  815.55   342.4  832.01   346.4  835.38   354.4  839.99   370.3  847.67
   394.2  861.62   430.1  883.97     454  896.92   473.9  909.54   489.8  920.86
#Mann= 3 , 0 , 0
       0     .08       0   286.6    .045       0   298.6      .1       0
Bank Sta=286.6,298.6
XS Rating Curve= 0 ,0
Exp/Cntr=0.3,0.1

Type RM Length L Ch R = 1 ,8888.8  ,27.2,26.1,24.6
XS GIS Cut Line= 4
     1713376.963      380387.128     1713577.657      380151.711
     1713640.852      380146.155     1713809.602      380019.072
#Sta/Elev= 30
       0  837.06    51.6  835.59    87.2  833.53     119  829.25   138.8  824.71
   158.6  822.25   166.6   819.4   170.5  818.82   182.4  820.16     230  818.68
   301.4  814.05   313.3  814.14   325.2     812   341.1   807.4     345  806.83
     349  807.01     353  808.34   360.9     812   376.8  813.04   380.8  814.74
   388.7  820.15   404.7  836.09   440.6  854.34   448.5  859.13   472.4  875.98
   512.3   899.8   536.2  913.21   540.2  915.76   556.1  928.83     584   948.2
#Mann= 3 , 0 , 0
       0     .08       0   341.1    .045       0     353      .1       0
Bank Sta=341.1,353
XS Rating Curve= 0 ,0
Exp/Cntr=0.3,0.1

Type RM Length L Ch R = 1 ,8862.7  ,55.5,47.3,40.3
XS GIS Cut Line= 4
     1713381.303      380412.301     1713581.998      380176.885
     1713645.192      380171.329     1713813.942      380044.246
#Sta/Elev= 30
       0  839.27    43.6  836.46    79.3  835.23   103.1  833.38   142.8  828.16
   170.5  822.43   186.4  820.54   198.3  818.25   210.2   817.8   222.1  818.37
   325.2  813.95   329.2  813.22     345  807.59     353  806.11   356.9  807.21
   364.9  811.22   372.8  812.09   384.8  812.22   392.7  814.76   396.7  818.08
   404.7  828.61   412.6   836.8   432.6  847.12   452.5  856.12   480.4  874.65
   512.3  893.12   532.2  906.29   548.2     915   560.1  924.91     584  941.42
#Mann= 3 , 0 , 0
       0     .08       0     345    .045       0   356.9      .1       0
Bank Sta=345,356.9
XS Rating Curve= 0 ,0
Exp/Cntr=0.3,0.1

Type RM Length L Ch R = 1 ,8815.4  ,95.2,91.7,88
XS GIS Cut Line= 3
     1713425.704      380408.438     1713601.486      380233.742
     1713922.666      380090.513
#Sta/Elev= 30
       0  837.64      64  833.18    95.9   828.5   143.9  819.48   179.9  816.69
   191.9  814.77   207.8  814.34   231.8  814.97   263.8  813.51   275.8  809.25
   287.8   806.1   291.8   805.7   295.8  806.46   303.8  809.62   307.8  810.57
   323.8  811.29   327.8  812.05   331.8  814.67   335.7  818.31   351.7  830.73
   363.7  838.11   379.7  848.88   415.7  864.74   439.6  876.23   471.6  898.06
   487.6  910.81   499.6  918.65   519.6     934   547.5  952.73   599.5  991.59
#Mann= 3 , 0 , 0
       0     .09       0   287.8    .045       0   295.8      .1       0
Bank Sta=287.8,295.8
XS Rating Curve= 0 ,0
Exp/Cntr=0.3,0.1

Type RM Length L Ch R = 1 ,8723.7  ,215.4,219.2,222.4
XS GIS Cut Line= 2
     1713316.039      380528.731     1713989.651      380103.383
#Sta/Elev= 30
       0  867.09    27.9  854.66    43.8   845.5    63.7  837.64    87.6  837.59
   111.5  838.77   143.4  837.51   191.2  834.07     231   827.8   282.8  817.42
   366.5  811.74   422.2   810.1   426.2  809.61   438.2  805.68   446.1  805.35
   450.1  806.37   458.1  810.34     470  810.96     474  812.96     486  825.97
   497.9  834.81   513.8  841.34   525.8   847.4   601.5  891.76   617.4   899.9
   633.4  910.21   653.3  924.98     729  973.76   752.8   986.2   796.7 1004.81
#Mann= 3 , 0 , 0
       0     .08       0   438.2    .045       0   450.1      .1       0
Bank Sta=438.2,450.1
XS Rating Curve= 0 ,0
Exp/Cntr=0.3,0.1

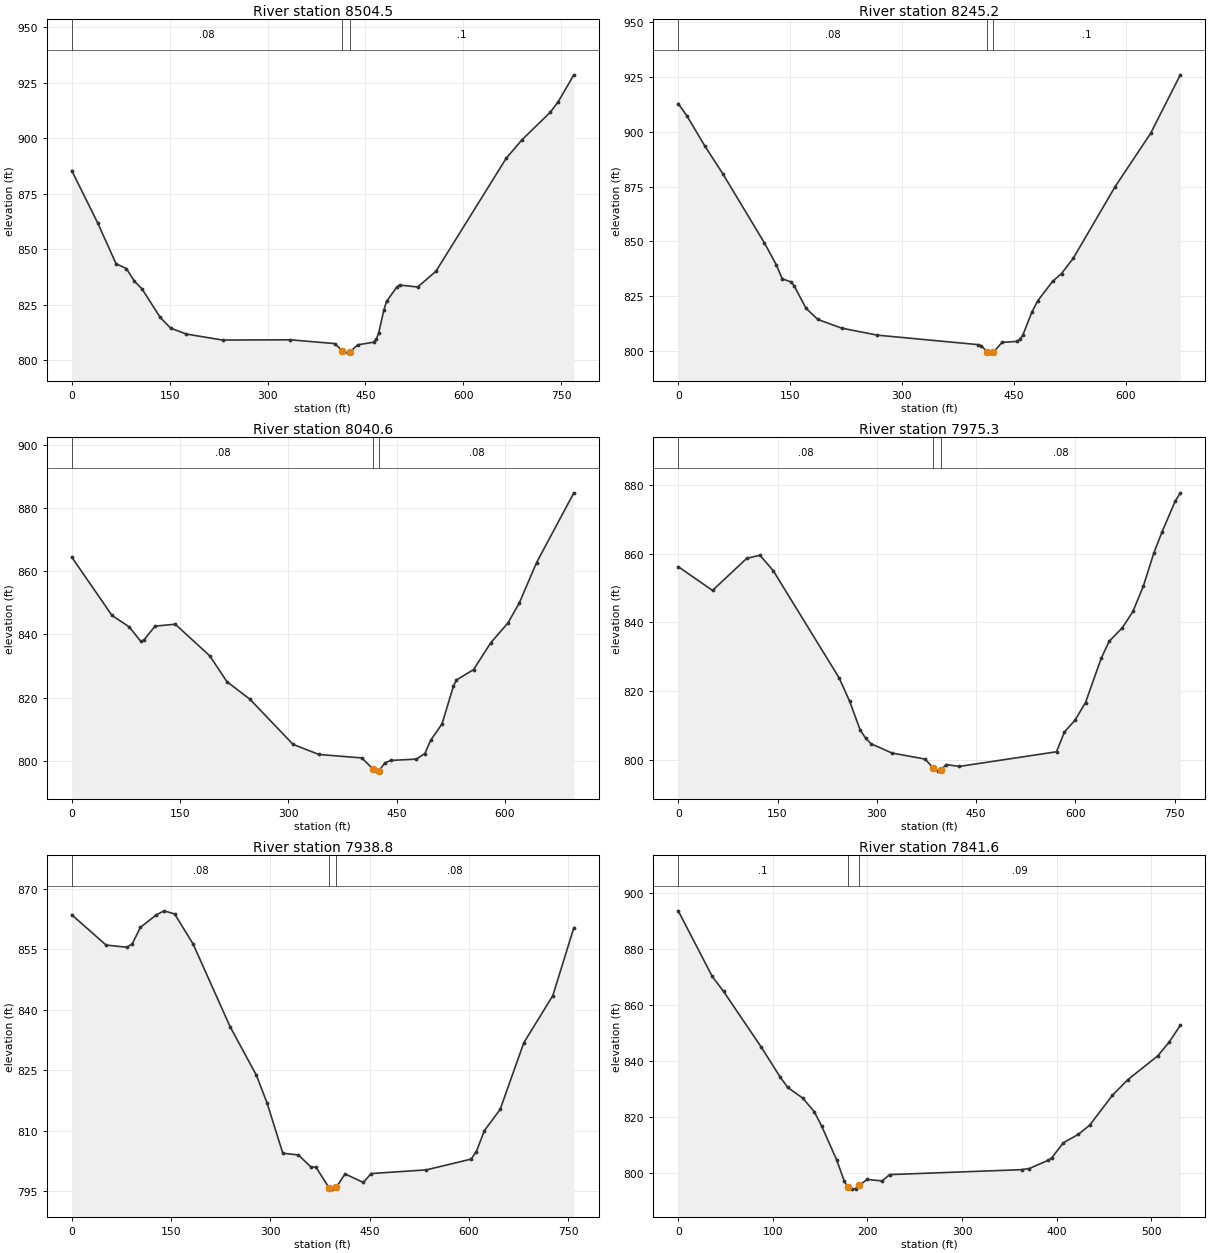
Type RM Length L Ch R = 1 ,8504.5  ,256.5,259.4,261.5
XS GIS Cut Line= 2
     1713402.845      380660.675     1714104.234      380344.703
#Sta/Elev= 30
       0  885.42    39.9  861.74    67.8  843.49    83.7  841.29    95.7  835.71
   107.6  832.15   135.5   819.3   151.5  814.46   175.4   811.8   231.2  809.09
   334.8  809.21   402.6  807.51   414.5  804.35   422.5   803.2   426.5  803.85
   438.4  806.96   462.4  808.11   466.4  809.35   470.3  812.37   478.3  822.69
   482.3  826.54   498.2  832.99   502.2  833.87   530.1  832.99     558  840.09
   665.6  890.96   689.6  899.24   733.4  911.79   745.4  916.48   769.3  928.58
#Mann= 3 , 0 , 0
       0     .08       0   414.5    .045       0   426.5      .1       0
Bank Sta=414.5,426.5
XS Rating Curve= 0 ,0
Exp/Cntr=0.3,0.1

Type RM Length L Ch R = 1 ,8245.2  ,198.5,204.5,211.4
XS GIS Cut Line= 2
     1713441.294      380875.247     1714079.315      380660.403
#Sta/Elev= 30
       0  912.85      12  907.05    35.8  893.46    59.8  880.83   115.5  849.38
   131.5  839.36   139.4  832.96   151.4  831.55   155.4  829.81   171.3  819.55
   187.2  814.44   219.1  810.49   266.9  807.29   402.3  802.96   406.3  802.48
   414.3  799.65   418.3  799.09   422.3  799.43   434.2  803.99   454.1  804.45
   458.1  805.31   462.1  807.34     474  817.65     482  822.94   501.9  831.79
   513.9  835.37   529.8  842.41   585.6  874.89   633.4  899.28   673.2  925.97
#Mann= 3 , 0 , 0
       0     .08       0   414.3    .045       0   422.3      .1       0
Bank Sta=414.3,422.3
XS Rating Curve= 0 ,0
Exp/Cntr=0.3,0.1

Type RM Length L Ch R = 1 ,8040.6  ,35.4,65.4,98.1
XS GIS Cut Line= 3
     1713463.754      381054.576     1713774.952      380943.898
     1714139.535      380926.971
#Sta/Elev= 30
       0  864.47    55.7     846    79.6  842.36    95.5  837.81    99.5  838.14
   115.4  842.61   143.3  843.22     191  833.23   214.9  825.01   246.7  819.45
   306.4  805.17   342.2  801.96   401.7  800.86   417.6  797.26   421.5  796.68
   425.5  796.81   433.4  799.25   441.4  800.06   477.1  800.48     489  802.26
   496.9   806.4   512.8  811.68   528.6  823.63   532.6  825.55   556.4  828.84
   580.2  837.34     604   843.6   619.9  850.02   643.7  862.75   695.3  884.84
#Mann= 3 , 0 , 0
       0     .08       0   417.6    .045       0   425.5     .08       0
Bank Sta=417.6,425.5
XS Rating Curve= 0 ,0
Exp/Cntr=0.3,0.1

Type RM Length L Ch R = 1 ,7975.3  ,37.8,36.5,36.8
XS GIS Cut Line= 6
     1713473.418      381075.467     1713789.391       380965.05
     1713823.418      380969.217     1713831.752      381012.272
     1713881.358       381044.38     1714157.446      380967.828
#Sta/Elev= 30
       0  856.18    51.8  849.26   103.6  858.62   123.5  859.48   143.4  855.04
   243.1  823.82     259  817.01   274.9  808.66   282.9  806.37   290.9  804.73
   322.8     802     373  800.24   384.9  797.66   392.9  796.74   396.9   797.2
   404.9  798.64   424.7  798.11   571.4  802.37   583.4  808.14   599.3  811.54
   615.2  816.68   639.1  829.64     651   834.5   670.9  838.43   686.8  843.16
   702.7  850.59   718.6  860.26   730.6  866.18   750.5  875.15   758.4  877.64
#Mann= 3 , 0 , 0
       0     .08       0   384.9    .045       0   396.9     .08       0
Bank Sta=384.9,396.9
XS Rating Curve= 0 ,0
Exp/Cntr=0.3,0.1

Type RM Length L Ch R = 1 ,7938.8  ,131.5,97.2,57.4
XS GIS Cut Line= 6
     1713443.036      381096.083     1713759.009      380985.666
     1713793.036      380989.833      1713801.37      381032.889
     1713850.976      381064.996     1714127.064      380988.444
#Sta/Elev= 30
       0  863.61    51.8  856.09    83.7  855.54    91.6  856.46   103.6  860.48
   127.5  863.57   139.5   864.6   155.4  863.82   183.3  856.35   239.1  835.82
   278.9  823.72   294.9  816.89   318.8  804.36   342.3  803.92   361.4  800.92
     369  800.85   388.9   795.7   392.9  795.43   399.6  795.89   412.8  799.21
   440.4  797.09   452.2   799.3   535.6  800.22   603.2  802.89   611.2  804.78
   623.2  809.96     647  815.23   682.8   831.8   726.6  843.52   758.4  860.41
#Mann= 3 , 0 , 0
       0     .08       0   388.9    .045       0   399.6     .08       0
Bank Sta=388.9,399.6
XS Rating Curve= 0 ,0
Exp/Cntr=0.3,0.1

Type RM Length L Ch R = 1 ,7841.6  ,360.3,354.7,348.2
XS GIS Cut Line= 2
     1713610.307      381146.376     1714120.724      381000.543
#Sta/Elev= 30
       0  893.61    35.9  870.19    47.9  864.82    87.8  844.89   107.8  834.19
   115.8  830.49   131.7  826.66   143.7  821.87   151.7  816.64   167.6  804.49
   175.6  796.95   179.6  794.74   183.6  794.15   187.6  794.34   191.6   795.5
   199.6  797.64   215.5  797.07   223.5  799.34   363.2  801.11   371.2  801.52
   391.2  804.46   395.1  805.43   407.1   810.7   423.1  813.74     435  817.02
     459  827.66     475  833.19   506.9  841.76   518.9  846.63   530.8   852.7
#Mann= 3 , 0 , 0
       0      .1       0   179.6    .045       0   191.6     .09       0
Bank Sta=179.6,191.6
XS Rating Curve= 0 ,0
Exp/Cntr=0.3,0.1

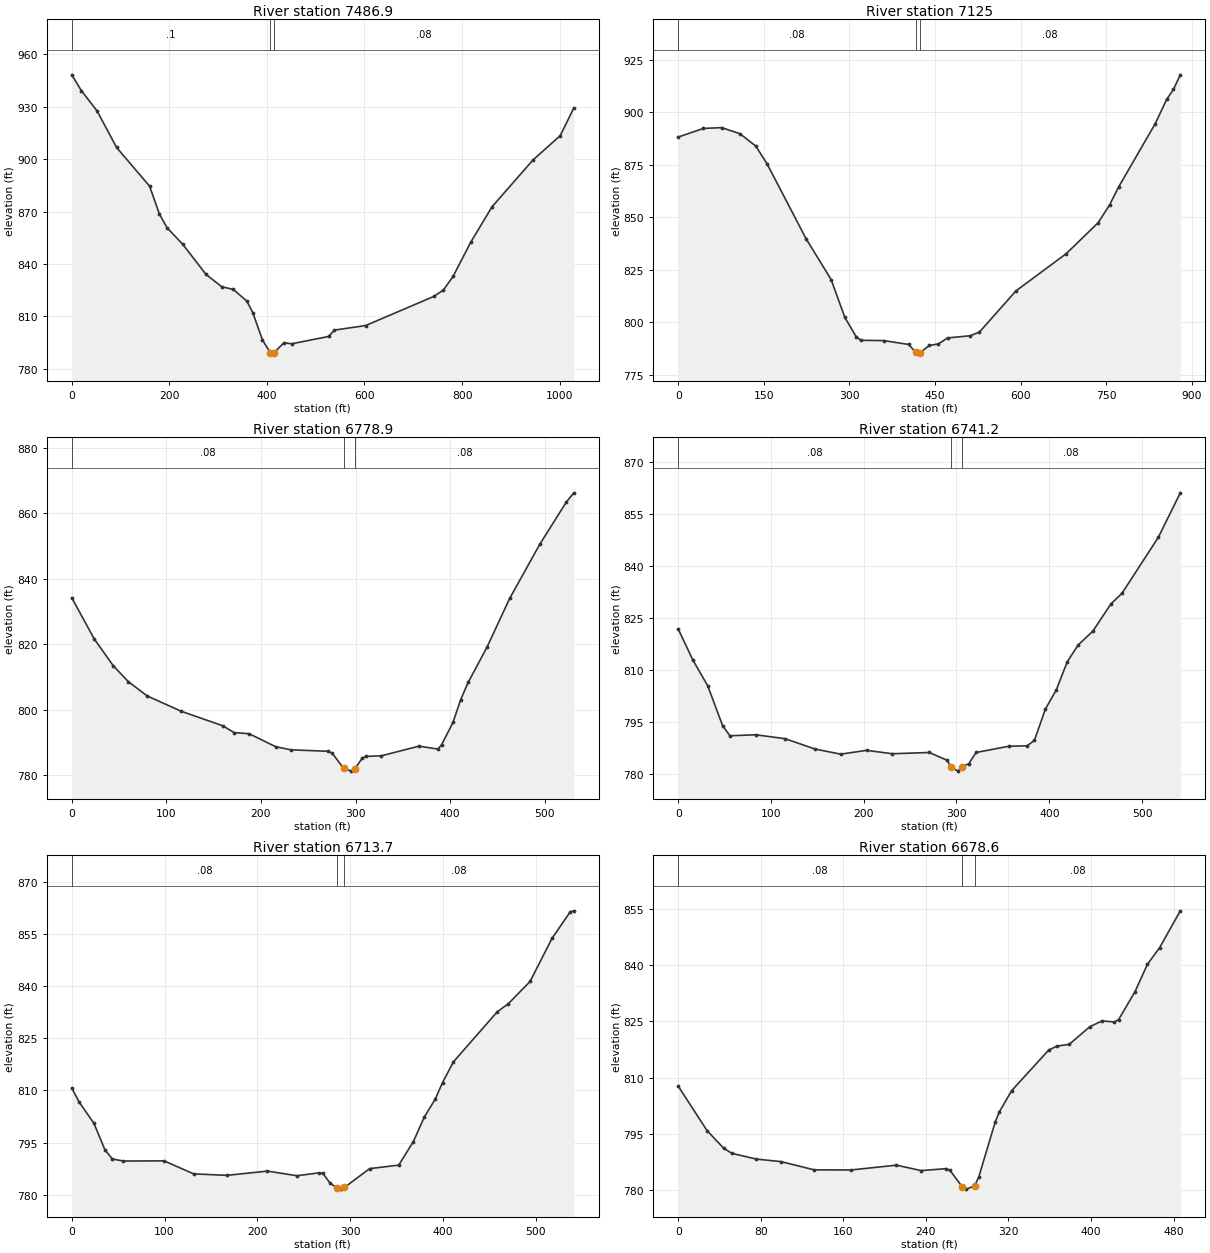
Type RM Length L Ch R = 1 ,7486.9  ,370.9,361.9,351.3
XS GIS Cut Line= 2
     1713563.652      381628.557     1714454.277      381112.932
#Sta/Elev= 30
       0  948.36    19.9   939.2    51.8  927.72    91.7  906.82   159.6  884.57
   179.5  868.75   195.4  860.76   227.4  851.35   275.2  834.07   307.1  827.07
   331.1  825.48     359  818.74     371  812.22   390.9  796.49   406.9  789.27
   410.8     789   414.8  789.26   434.8  794.94   450.7  794.35   526.5  798.54
   538.5   802.2   602.3  804.78   741.9  821.45   761.9  825.16   781.8  833.06
   817.7  852.49   861.6  872.87   945.4  899.62  1001.2  913.54  1029.1  929.41
#Mann= 3 , 0 , 0
       0      .1       0   406.9    .045       0   414.8     .08       0
Bank Sta=406.9,414.8
XS Rating Curve= 0 ,0
Exp/Cntr=0.3,0.1

Type RM Length L Ch R = 1 ,7125    ,337.9,346.1,355.3
XS GIS Cut Line= 2
      1713909.92      382018.705     1714429.538      381308.548
#Sta/Elev= 30
       0  888.28      44  892.37      76  892.76     108   889.9     136  883.96
     156  875.37     224  839.86     268  820.38     292  802.36     312  793.11
     320  791.45     360   791.3     404  789.46     416  785.75     420  785.33
     424   785.6     440  788.98     456  789.72     472  792.57     512  793.61
     528  795.39     592     815     680   832.7     736  847.46     756  855.92
     772  864.56     836  894.62     856  906.17     868  910.97     880  917.92
#Mann= 3 , 0 , 0
       0     .08       0     416    .045       0     424     .08       0
Bank Sta=416,424
XS Rating Curve= 0 ,0
Exp/Cntr=0.3,0.1

Type RM Length L Ch R = 1 ,6778.9  ,63.1,37.7,23.2
XS GIS Cut Line= 2
     1714119.902      382100.519     1714566.083      381813.192
#Sta/Elev= 30
       0  834.14    23.9  821.53    43.9  813.38    59.8  808.53    79.8  804.17
   115.7   799.5   159.6  795.07   171.6  792.99   187.5  792.64   215.5  788.68
   231.4  787.74   271.3  787.27   275.3  786.72   287.3  782.06   295.3  781.22
   299.3  781.96   307.2  785.24   311.2  785.72   327.2   785.9   367.1  788.85
     387  787.95     391  789.32     403  796.12     411  802.99     419  808.32
   438.9  819.06   462.9  833.97   494.8  850.54   522.7  863.36   530.7   866.2
#Mann= 3 , 0 , 0
       0     .08       0   287.3    .045       0   299.3     .08       0
Bank Sta=287.3,299.3
XS Rating Curve= 0 ,0
Exp/Cntr=0.3,0.1

Type RM Length L Ch R = 1 ,6741.2  ,20.5,27.5,19
XS GIS Cut Line= 4
     1714188.652      382173.609     1714395.944      381993.401
      1714387.09      381955.901     1714579.277      381832.984
#Sta/Elev= 30
       0   821.9    15.9   812.9    31.8  805.52    47.8  794.04    55.7   791.1
    83.6  791.38   115.4  790.25   147.3  787.27   175.2  785.79     203  786.89
   230.9  785.91   270.7  786.27   290.1  783.99   293.9  782.06   301.6  780.89
   305.5  782.18   313.2     783   321.1  786.27   356.5  788.08   376.1   788.2
     384  789.75   395.8  798.78   407.6  804.34   419.4  812.45   431.2  817.31
   446.9  821.25   466.6  829.19   478.4  832.21   517.7  848.42   541.3  861.22
#Mann= 3 , 0 , 0
       0     .08       0   293.9    .045       0   305.5     .08       0
Bank Sta=293.9,305.5
XS Rating Curve= 0 ,0
Exp/Cntr=0.3,0.1

Type RM Length L Ch R = 1 ,6713.7  ,11.5,35.1,62.8
XS GIS Cut Line= 4
     1714211.048      382179.859      1714418.34      381999.651
     1714409.486      381962.151     1714601.673      381839.234
#Sta/Elev= 30
       0  810.69       8  806.65    23.9  800.53    35.8  792.86    43.8  790.24
    55.7  789.66    99.5  789.71   131.4  785.96   167.2  785.53     211  786.76
   242.8  785.42   266.7  786.26   270.7  786.12   278.5  783.28   286.2  781.85
   290.1  781.56   293.9  782.03   321.1  787.47   352.5  788.48   368.3  795.27
   380.1  802.36   391.9  807.52   399.7  812.27   411.5  818.26   458.7  832.67
   470.5  834.96   494.1  841.42   517.7  853.81   537.4  861.49   541.3  861.78
#Mann= 3 , 0 , 0
       0     .08       0   286.2    .045       0   293.9     .08       0
Bank Sta=286.2,293.9
XS Rating Curve= 0 ,0
Exp/Cntr=0.3,0.1

Type RM Length L Ch R = 1 ,6678.6  ,274.6,269.9,263.9
XS GIS Cut Line= 3
     1714223.201      382189.929     1714409.833      382021.526
     1714627.715      381932.984
#Sta/Elev= 30
       0  807.72    27.9  795.87    43.9   791.2    51.9   789.8    75.8  788.26
    99.8  787.58   131.7  785.39   167.6  785.36   211.5  786.64   235.4   785.2
   259.4   785.7   263.3  785.28   275.3  780.85   279.3  780.25   287.2  781.13
   291.2  783.42   307.2  798.16   311.2  800.86   323.1  806.51     359  817.33
     367   818.4   378.9  818.86   398.9  823.58   410.8  825.11   422.8  824.84
   426.8  825.48   442.7  832.91   454.7   840.2   466.6  844.68   486.6  854.48
#Mann= 3 , 0 , 0
       0     .08       0   275.3    .045       0   287.2     .08       0
Bank Sta=275.3,287.2
XS Rating Curve= 0 ,0
Exp/Cntr=0.3,0.1

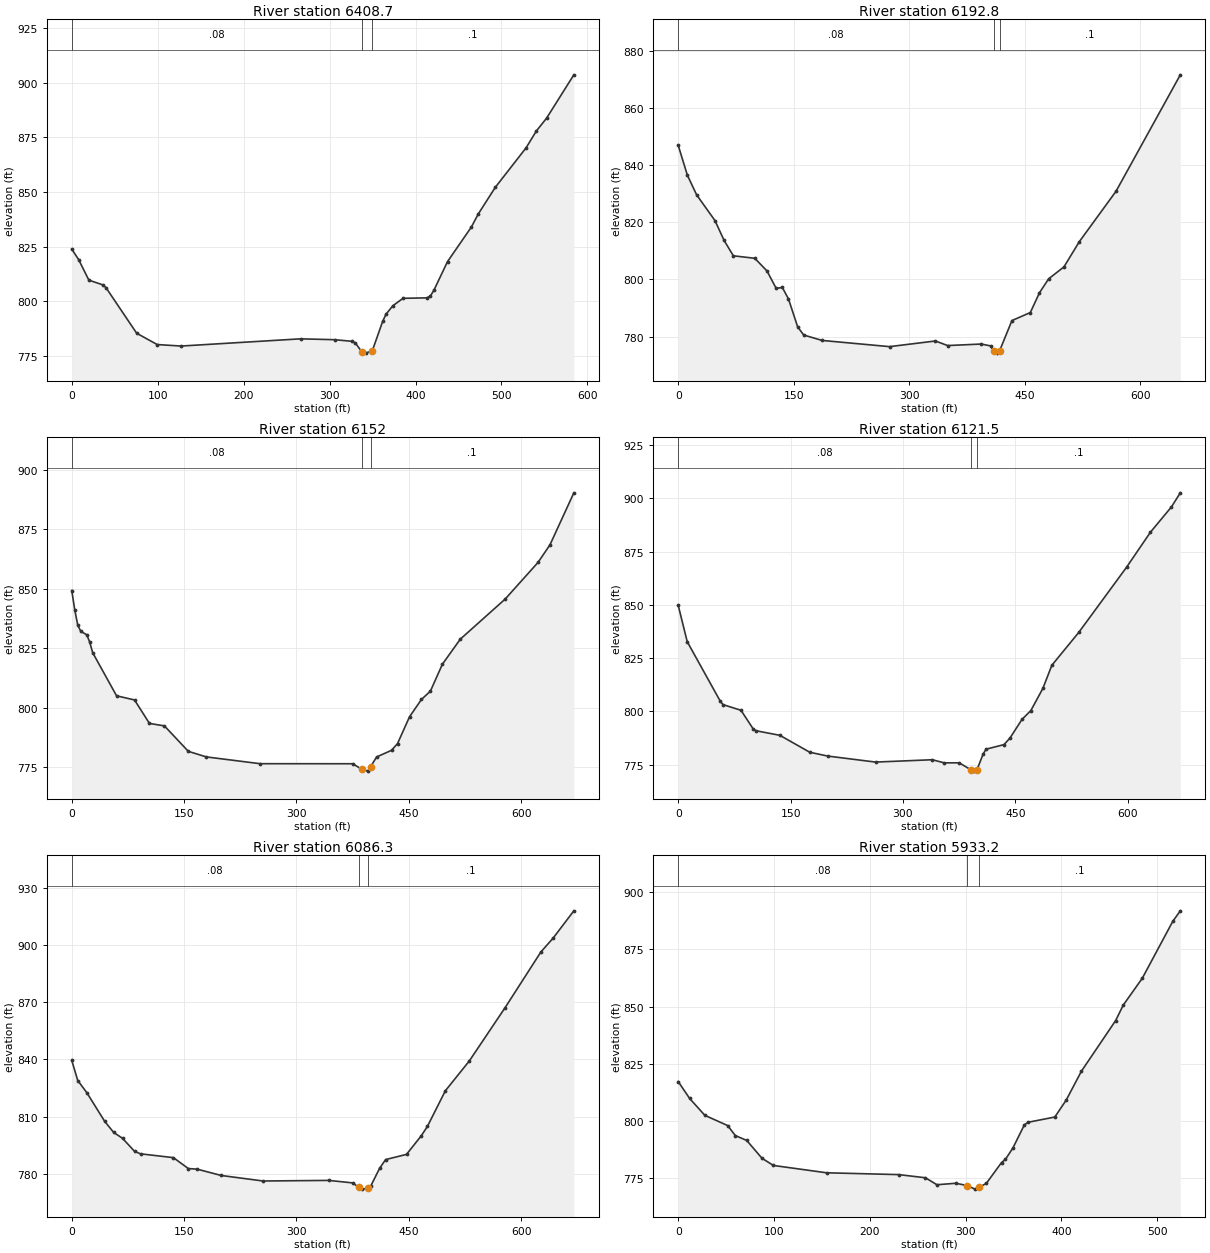
Type RM Length L Ch R = 1 ,6408.7  ,215.2,215.8,216.1
XS GIS Cut Line= 2
     1714299.584      382408.407     1714791.121      382092.651
#Sta/Elev= 30
       0  823.89       8  819.11    19.9   809.7    35.8  807.59    39.7  806.34
    75.5  785.43    99.4  780.24   127.2  779.56   266.3  782.86     306  782.46
   325.9  781.73   329.9     781   337.8  776.76   341.8  776.32   349.7   777.4
   361.7  790.79   365.6  794.11   373.6     798   385.5   801.4   413.3   801.6
   417.3  802.46   421.3  805.03   437.2  818.18     465  834.02   472.9  839.92
   492.8  852.16   528.6  870.22   540.5  877.89   552.4  883.76   584.2  903.63
#Mann= 3 , 0 , 0
       0     .08       0   337.8    .045       0   349.7      .1       0
Bank Sta=337.8,349.7
XS Rating Curve= 0 ,0
Exp/Cntr=0.3,0.1

Type RM Length L Ch R = 1 ,6192.8  ,40.7,40.8,40.8
XS GIS Cut Line= 2
     1714340.388      382629.599     1714895.076      382286.717
#Sta/Elev= 30
       0  846.92    11.9  836.48    23.9  829.62    47.7  820.62    59.6  813.66
    71.6  808.29    99.4  807.42   115.3  802.98   127.2  796.89   135.2  797.21
   143.2  793.18   155.1  783.42     163  780.55   186.9  778.66   274.4  776.49
     334  778.47   349.9  776.87   393.6   777.4   405.6  776.75   409.6  775.04
   413.5  774.22   417.5  775.11   433.4  785.61   457.3  788.43   469.2  795.36
   481.1  800.24     501  804.41   520.9  813.23   568.6  830.88   652.1  871.64
#Mann= 3 , 0 , 0
       0     .08       0   409.6    .045       0   417.5      .1       0
Bank Sta=409.6,417.5
XS Rating Curve= 0 ,0
Exp/Cntr=0.3,0.1

Type RM Length L Ch R = 1 ,6152    ,30.4,30.5,30.7
XS GIS Cut Line= 2
     1714377.709      382653.632     1714948.456       382302.07
#Sta/Elev= 30
       0  849.18       4  841.03       8  834.67      12  832.06      20  830.61
    23.9   827.6    27.9   823.1    59.8  804.99    83.8  803.24   103.7  793.39
   123.7  792.35   155.6  781.67   179.6  779.33   251.4  776.48   375.1  776.46
     387  774.19     395  773.36     399  775.22     407  779.31   426.9   782.1
   434.9  784.92   450.9  796.16   466.8  803.44   478.8  806.95   494.8  818.24
   518.7  828.77   578.6   845.6   622.4  860.96   638.4  868.36   670.3  890.21
#Mann= 3 , 0 , 0
       0     .08       0     387    .045       0     399      .1       0
Bank Sta=387,399
XS Rating Curve= 0 ,0
Exp/Cntr=0.3,0.1

Type RM Length L Ch R = 1 ,6121.5  ,35.3,35.2,35.2
XS GIS Cut Line= 2
       1714392.9      382679.674     1714963.647      382328.111
#Sta/Elev= 30
       0  849.74      12   832.7    55.9  804.88    59.8  803.14    83.8  800.47
    99.8  791.87   103.7  790.88   135.7  788.72   175.6  780.77   199.5  778.98
   263.4  776.15   339.2  777.25   355.1  775.79   375.1   775.8     391  772.47
     395   771.9     399  772.64     407   779.9     411   782.2   434.9  784.36
   442.9  787.44   458.9  796.18   470.8  800.37   486.8  810.75   498.8  821.63
   534.7  837.04   598.5  867.65   630.4  884.12   658.4  895.98   670.3  902.62
#Mann= 3 , 0 , 0
       0     .08       0     391    .045       0     399      .1       0
Bank Sta=391,399
XS Rating Curve= 0 ,0
Exp/Cntr=0.3,0.1

Type RM Length L Ch R = 1 ,6086.3  ,156,153.1,150.3
XS GIS Cut Line= 2
     1714414.602      382706.801     1714985.348      382355.238
#Sta/Elev= 30
       0  839.47       8  828.96      20  822.65    43.9   807.6    55.9  801.78
    67.8  798.67    83.8  791.86    91.8  790.56   135.7  788.55   155.6  782.84
   167.6  782.51   199.5  779.21   255.4  776.32   343.2  776.63   375.1  775.32
     383  773.01     387  772.06     395  772.44     399  773.55     411  782.97
     419  787.54   446.9  790.26   466.8  800.11   474.8  804.93   498.8  823.61
   530.7  839.19   578.6  867.18   626.4  896.37   642.4  903.45   670.3  917.86
#Mann= 3 , 0 , 0
       0     .08       0     383    .045       0     395      .1       0
Bank Sta=383,395
XS Rating Curve= 0 ,0
Exp/Cntr=0.3,0.1

Type RM Length L Ch R = 1 ,5933.2  ,263,258.2,252.5
XS GIS Cut Line= 2
     1714594.729      382818.401     1715002.715      382489.408
#Sta/Elev= 30
       0  817.27    11.9   809.9    27.8  802.52    51.6  798.05    59.6  793.68
    71.5  791.56    87.4  783.77    99.3  780.63   154.8  777.42   230.3  776.62
   258.1  775.24     270   772.2   289.8  772.84   301.8  771.82   309.7  770.28
   313.7  771.01   321.6  772.78   337.5  781.91   341.5  783.26   349.4  788.28
   361.3  798.37   365.3   799.5   393.1  801.78     405  809.19   420.9  821.83
   456.6  843.94   464.6  850.72   484.4  862.42   516.2  887.26   524.1  891.88
#Mann= 3 , 0 , 0
       0     .08       0   301.8    .045       0   313.7      .1       0
Bank Sta=301.8,313.7
XS Rating Curve= 0 ,0
Exp/Cntr=0.3,0.1

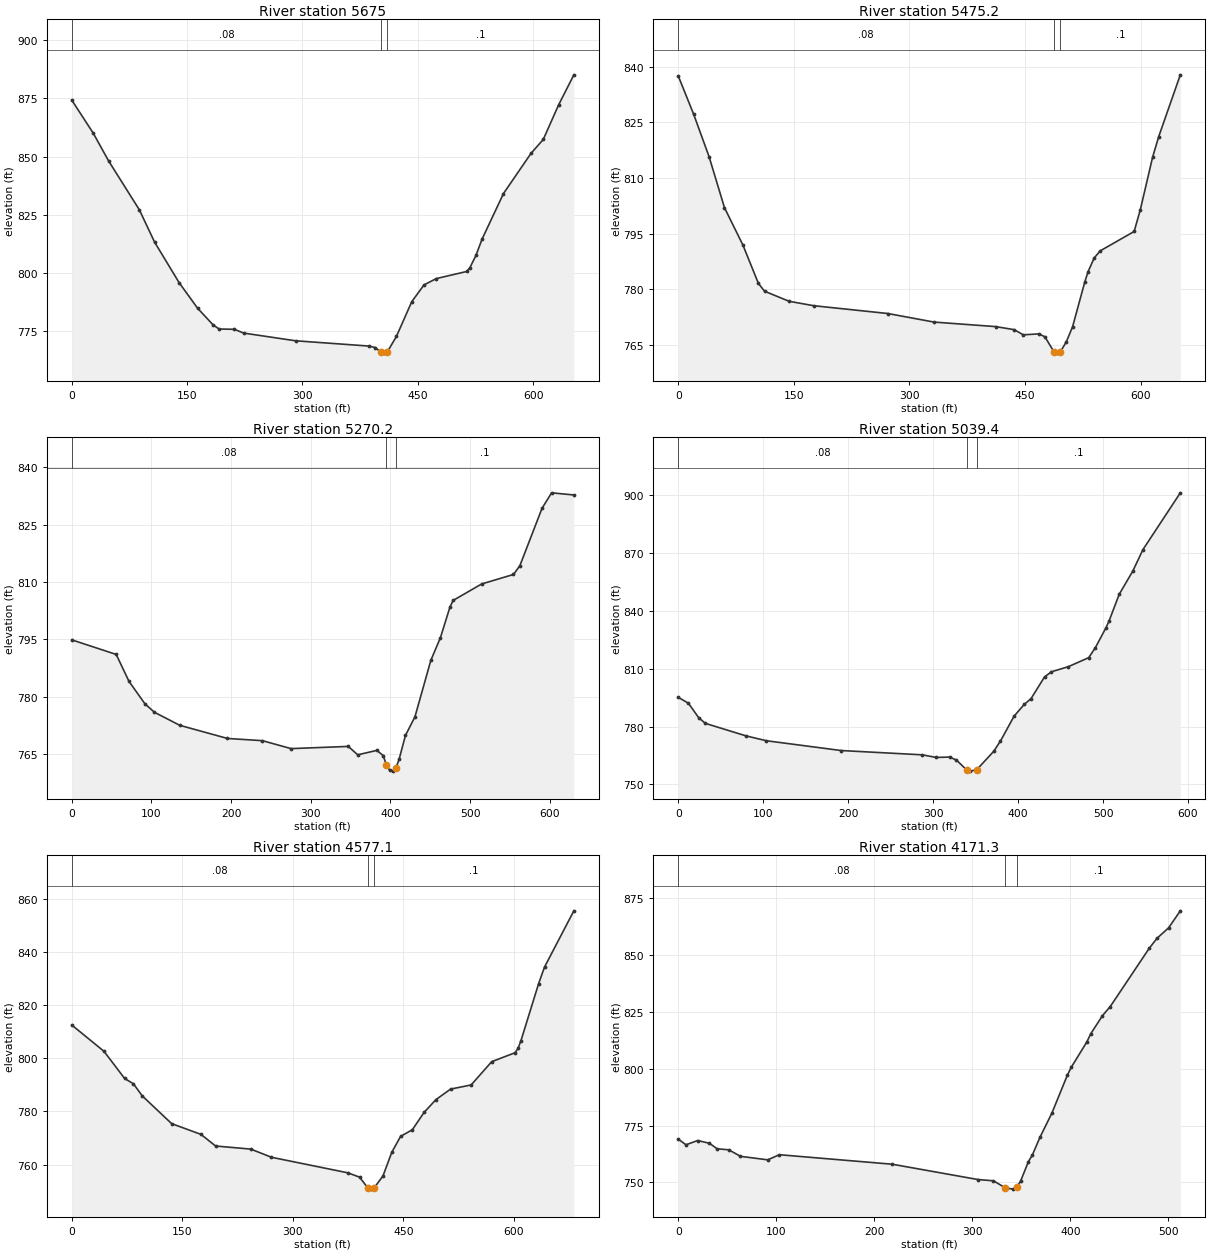
Type RM Length L Ch R = 1 ,5675    ,205.8,199.8,193.2
XS GIS Cut Line= 3
     1714644.208       383019.79     1714845.597      382990.276
     1715132.055      382643.922
#Sta/Elev= 30
       0  874.27    27.9  860.08    47.9  848.13    87.8  827.16   107.8  813.16
   139.7  795.74   163.6   784.8   183.6  777.69   191.6  775.84   211.5  775.72
   223.4   774.1     291  770.78   386.5  768.51   394.5  767.88   402.4  765.85
   406.4  765.47   410.4  765.98   422.3  772.69   442.2   787.6   458.1  794.79
     474  797.52   513.8  800.59   517.8  802.21   525.7  807.51   533.7  814.55
   561.5  834.11   597.3  851.38   613.2  857.34   633.1  872.15     653  885.15
#Mann= 3 , 0 , 0
       0     .08       0   402.4    .045       0   410.4      .1       0
Bank Sta=402.4,410.4
XS Rating Curve= 0 ,0
Exp/Cntr=0.3,0.1

Type RM Length L Ch R = 1 ,5475.2  ,201.3,205.1,208.1
XS GIS Cut Line= 3
     1714704.972      383119.616     1715095.597      383033.679
     1715203.236      382806.248
#Sta/Elev= 30
       0  837.52      20  827.19      40  815.76      60     802      84  791.89
     104   781.6     112  779.47     144  776.75     176  775.56     272  773.46
     332  771.15     412  769.93   435.9  769.11   447.9  767.71   467.9  767.97
   475.8   767.2   487.8  763.08   491.8  762.78   495.8  763.07   503.8  765.89
   511.8   769.9   527.8  782.09   531.8  784.68   539.8  788.43   547.7  790.36
   591.7  795.58   599.7  801.45   615.6  815.57   623.6  821.17   651.6  837.81
#Mann= 3 , 0 , 0
       0     .08       0   487.8    .045       0   495.8      .1       0
Bank Sta=487.8,495.8
XS Rating Curve= 0 ,0
Exp/Cntr=0.3,0.1

Type RM Length L Ch R = 1 ,5270.2  ,220.6,230.7,239.6
XS GIS Cut Line= 2
     1715083.444      383380.901     1715430.666      382854.859
#Sta/Elev= 30
       0  794.85    55.8  791.03    71.8     784    91.8  778.12   103.7  775.91
   135.6  772.48   195.5  769.04   239.4  768.46   275.3  766.38   347.1  766.96
     359  764.76     383  765.92     391  764.55   394.9  762.16   398.9  760.74
   402.9  760.49   406.9  761.34   410.9  763.55   418.9  769.84   430.8  774.69
   450.8   789.5   462.8  795.42   474.7  803.39   478.7  805.16   514.6  809.48
   554.5  811.96   562.5  814.24   590.4   829.3   602.4  833.33   630.3  832.77
#Mann= 3 , 0 , 0
       0     .08       0   394.9    .045       0   406.9      .1       0
Bank Sta=394.9,406.9
XS Rating Curve= 0 ,0
Exp/Cntr=0.3,0.1

Type RM Length L Ch R = 1 ,5039.4  ,468.9,462.3,455.8
XS GIS Cut Line= 2
     1715162.003      383419.963     1715646.378      383081.422
#Sta/Elev= 30
       0  795.16      12  792.07      24  784.63    31.9  781.63    79.9  775.14
   103.8  772.63   191.7  767.56   287.5  765.32   303.5  763.98   319.4  764.16
   327.4  762.64   339.4  757.55   343.4  756.88   351.4  757.63   371.3  767.11
   379.3  772.49   395.3  785.35   407.3  791.47   415.3  794.48   431.2   805.7
   439.2  808.35   459.2  811.03   483.2   815.7   491.1  820.94   503.1  830.84
   507.1  834.67   519.1  848.55   535.1  860.59     547  871.69     591  901.13
#Mann= 3 , 0 , 0
       0     .08       0   339.4    .045       0   351.4      .1       0
Bank Sta=339.4,351.4
XS Rating Curve= 0 ,0
Exp/Cntr=0.3,0.1

Type RM Length L Ch R = 1 ,4577.1  ,423.1,405.8,388.7
XS GIS Cut Line= 2
     1715466.034       383891.74     1715900.062      383366.566
#Sta/Elev= 30
       0  812.51    43.8   802.6    71.7  792.42    83.7  790.41    95.6  785.88
   135.5  775.44   175.3   771.4   195.2  767.03     243  765.86   270.9   762.8
   374.5  756.96   390.5  755.32   402.4  751.06   406.4  750.82   410.4  751.31
   422.3  755.78   434.3  764.69   446.2  770.64   462.2  773.16   478.1  779.67
     494  784.43     514  788.42   541.9  789.97   569.8  798.72   601.6   802.1
   605.6  803.74   609.6  806.68   633.5  828.06   641.5  834.29   681.3  855.43
#Mann= 3 , 0 , 0
       0     .08       0   402.4    .045       0   410.4      .1       0
Bank Sta=402.4,410.4
XS Rating Curve= 0 ,0
Exp/Cntr=0.3,0.1

Type RM Length L Ch R = 1 ,4171.3  ,448.1,445,441.7
XS GIS Cut Line= 2
     1716106.225      383987.226     1716110.565      383475.073
#Sta/Elev= 30
       0  769.08     7.9  766.58    19.8  768.45    31.8  767.25    39.7  764.82
    51.6  764.37    63.5   761.5    91.3  759.96   103.2  762.21   218.4  758.03
   305.7   751.3   321.6  750.74   333.5  747.68   341.4  747.08   345.4   747.8
   349.4  750.75   357.3  759.23   361.3  762.11   369.2  770.04   381.2  780.52
     397  797.22     401  800.71   416.9  811.85   420.8  815.38   432.8  823.37
   440.7  827.35   480.4  852.94   488.4  857.38   500.3  862.01   512.2  869.47
#Mann= 3 , 0 , 0
       0     .08       0   333.5    .045       0   345.4      .1       0
Bank Sta=333.5,345.4
XS Rating Curve= 0 ,0
Exp/Cntr=0.3,0.1

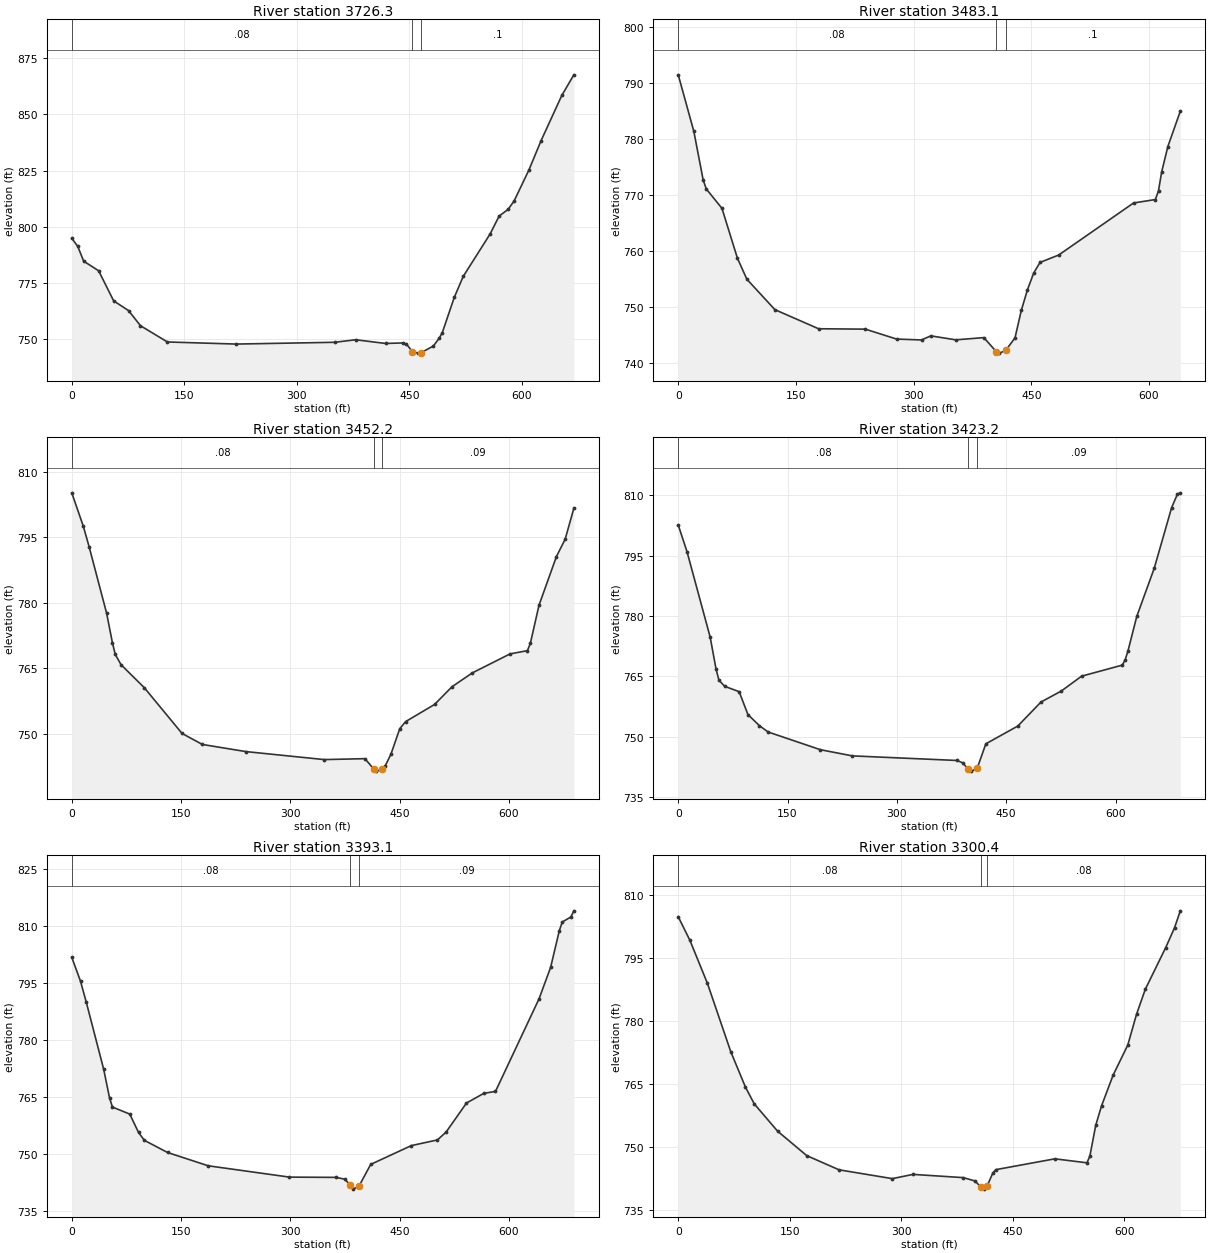
Type RM Length L Ch R = 1 ,3726.3  ,233.7,243.2,252.6
XS GIS Cut Line= 2
     1716600.805      384045.831     1716517.472      383381.769
#Sta/Elev= 30
       0  794.95       8  791.32    15.9  784.76    35.8  780.51    55.8  767.14
    75.7  762.79    91.6  756.07   127.5  748.84   219.1  747.91   350.6   748.7
   378.5  749.83   418.3  748.18   442.2  748.42   446.2  747.85   454.2  744.52
   462.1  743.88   466.1  744.15     482  747.03     490   750.6     494  753.05
   509.9  768.67   521.9  778.03   557.7  796.88   569.7  804.82   581.6  807.79
   589.6  811.48   609.5  825.38   625.4   838.2   653.3   858.5   669.3  867.63
#Mann= 3 , 0 , 0
       0     .08       0   454.2    .045       0   466.1      .1       0
Bank Sta=454.2,466.1
XS Rating Curve= 0 ,0
Exp/Cntr=0.3,0.1

Type RM Length L Ch R = 1 ,3483.1  ,32.8,30.9,28.8
XS GIS Cut Line= 2
     1716669.381      384047.567     1716829.104      383427.776
#Sta/Elev= 30
       0  791.51    19.9  781.41    31.8  772.73    35.8  771.13    55.7  767.69
    75.5  758.76    87.5  755.03   123.2   749.6   178.9  746.19   238.5  746.12
   278.3  744.35   310.1  744.19     322  744.92   353.8  744.21   389.6  744.61
   405.5  742.09   409.5  741.84   417.4  742.32   429.3  744.57   437.3  749.46
   445.2  753.17   453.2  756.16   461.2  758.03     485  759.35   580.4  768.64
   608.2  769.25   612.2  770.82   616.2  774.16   624.1   778.7     640  785.02
#Mann= 3 , 0 , 0
       0     .08       0   405.5    .045       0   417.4      .1       0
Bank Sta=405.5,417.4
XS Rating Curve= 0 ,0
Exp/Cntr=0.3,0.1

Type RM Length L Ch R = 1 ,3452.2  ,28.9,29,28.9
XS GIS Cut Line= 2
     1716724.069      384079.685     1716846.465      383401.734
#Sta/Elev= 30
       0  805.14    15.9  797.46    23.9  792.75    47.8  777.61    55.8  770.83
    59.7  768.16    67.7  765.81    99.6  760.55   151.3   750.1   179.2  747.58
   238.9  745.95   346.4  744.12   402.2  744.33   414.1  742.02   418.1  741.48
   426.1  741.93   430.1  742.68     438  745.38     450  751.17     458   752.8
   497.8  756.73   521.7  760.78   549.5  763.94   601.3  768.29   625.2  769.04
   629.2  770.69   641.1  779.43     665  790.56     677  794.54   688.9   801.6
#Mann= 3 , 0 , 0
       0     .08       0   414.1    .045       0   426.1     .09       0
Bank Sta=414.1,426.1
XS Rating Curve= 0 ,0
Exp/Cntr=0.3,0.1

Type RM Length L Ch R = 1 ,3423.2  ,30.1,30.1,30.3
XS GIS Cut Line= 2
     1716752.715      384076.213     1716875.111      383398.262
#Sta/Elev= 30
       0   802.6      12     796    43.8  774.76    51.8   766.9    55.8  764.07
    63.7  762.52    83.6  761.19    95.6  755.52   111.5  752.72   123.4  751.17
   195.1  746.77   238.9  745.24   382.3   744.1   390.2  743.53   398.2  741.87
   402.2  741.45   410.2  742.17   422.1  748.24   465.9  752.65   497.8  758.63
   525.6  761.35   553.5  765.05   609.3  767.79   613.2  769.07   617.2   771.4
   629.2  779.91   653.1  791.84     677  806.93   684.9  810.26   688.9   810.6
#Mann= 3 , 0 , 0
       0     .08       0   398.2    .045       0   410.2     .09       0
Bank Sta=398.2,410.2
XS Rating Curve= 0 ,0
Exp/Cntr=0.3,0.1

Type RM Length L Ch R = 1 ,3393.1  ,100.5,92.7,84.9
XS GIS Cut Line= 2
     1716782.229      384075.345     1716904.625      383397.394
#Sta/Elev= 30
       0  801.75      12  795.47    19.9  789.96    43.8  772.29    51.8   764.8
    55.8  762.36    79.6  760.51    91.6  755.68    99.6  753.61   131.4  750.41
   187.2  746.91   298.7  743.93   362.4  743.86   374.3   743.4   382.3  741.87
   386.3  740.77   394.2  741.59   410.2  747.28   465.9  752.22   501.8  753.72
   513.7   755.8   541.6  763.42   565.5  765.98   581.4  766.48   641.1  790.82
     657  799.09     669  808.79     673  811.04   684.9  812.39   688.9  813.99
#Mann= 3 , 0 , 0
       0     .08       0   382.3    .045       0   394.2     .09       0
Bank Sta=382.3,394.2
XS Rating Curve= 0 ,0
Exp/Cntr=0.3,0.1

Type RM Length L Ch R = 1 ,3300.4  ,44.3,32.3,19.2
XS GIS Cut Line= 4
     1716932.402      384103.123     1716972.333      383914.755
     1716930.666      383615.276     1716926.326       383434.72
#Sta/Elev= 30
       0  804.81    15.7  799.19    39.3  788.93    70.7  772.65    90.4  764.24
   102.2  760.25   133.6  753.74   172.9   747.9   216.4  744.52     288  742.42
   315.9  743.43   383.5  742.66   399.4  741.86   407.4  740.37   411.4  739.92
   415.4   740.6   423.3  743.77   427.3  744.56   506.7  747.14   549.9  746.19
   553.8  747.79   561.7  755.11   569.5  759.75   585.2  767.12   604.8  774.23
   616.6  781.58   628.4  787.53   655.9  797.48   667.7  802.17   675.5  806.22
#Mann= 3 , 0 , 0
       0     .08       0   407.4    .045       0   415.4     .08       0
Bank Sta=407.4,415.4
XS Rating Curve= 0 ,0
Exp/Cntr=0.3,0.1