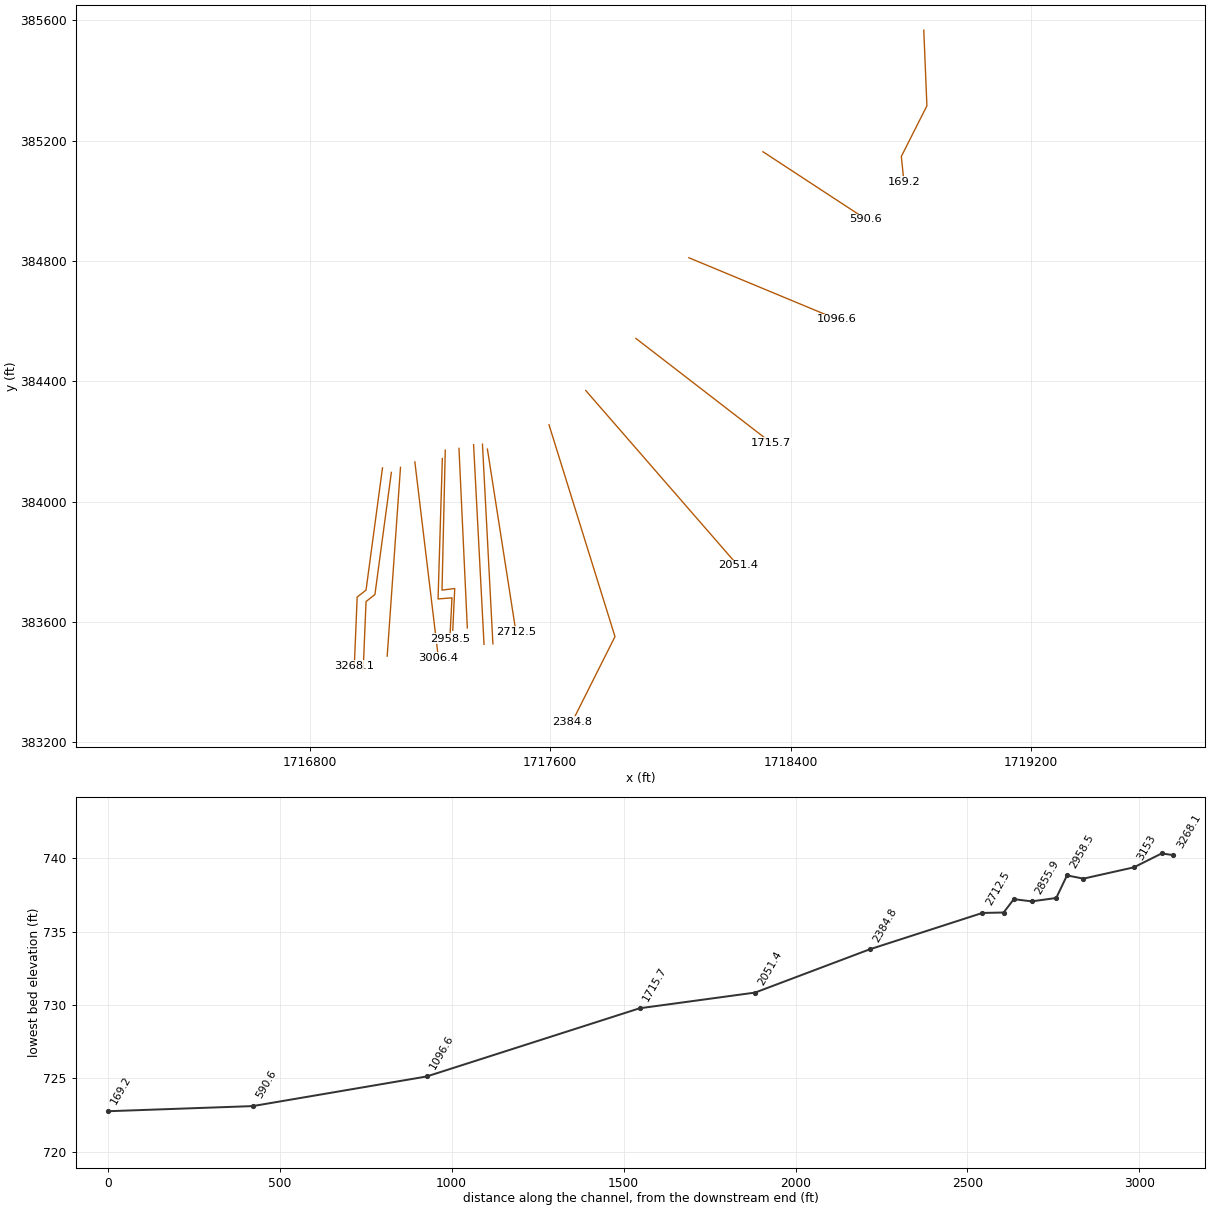
HEC-RAS study MUDFK.prj: MUDFK

--- MUDFK.g01 (geometry) --- (continued)

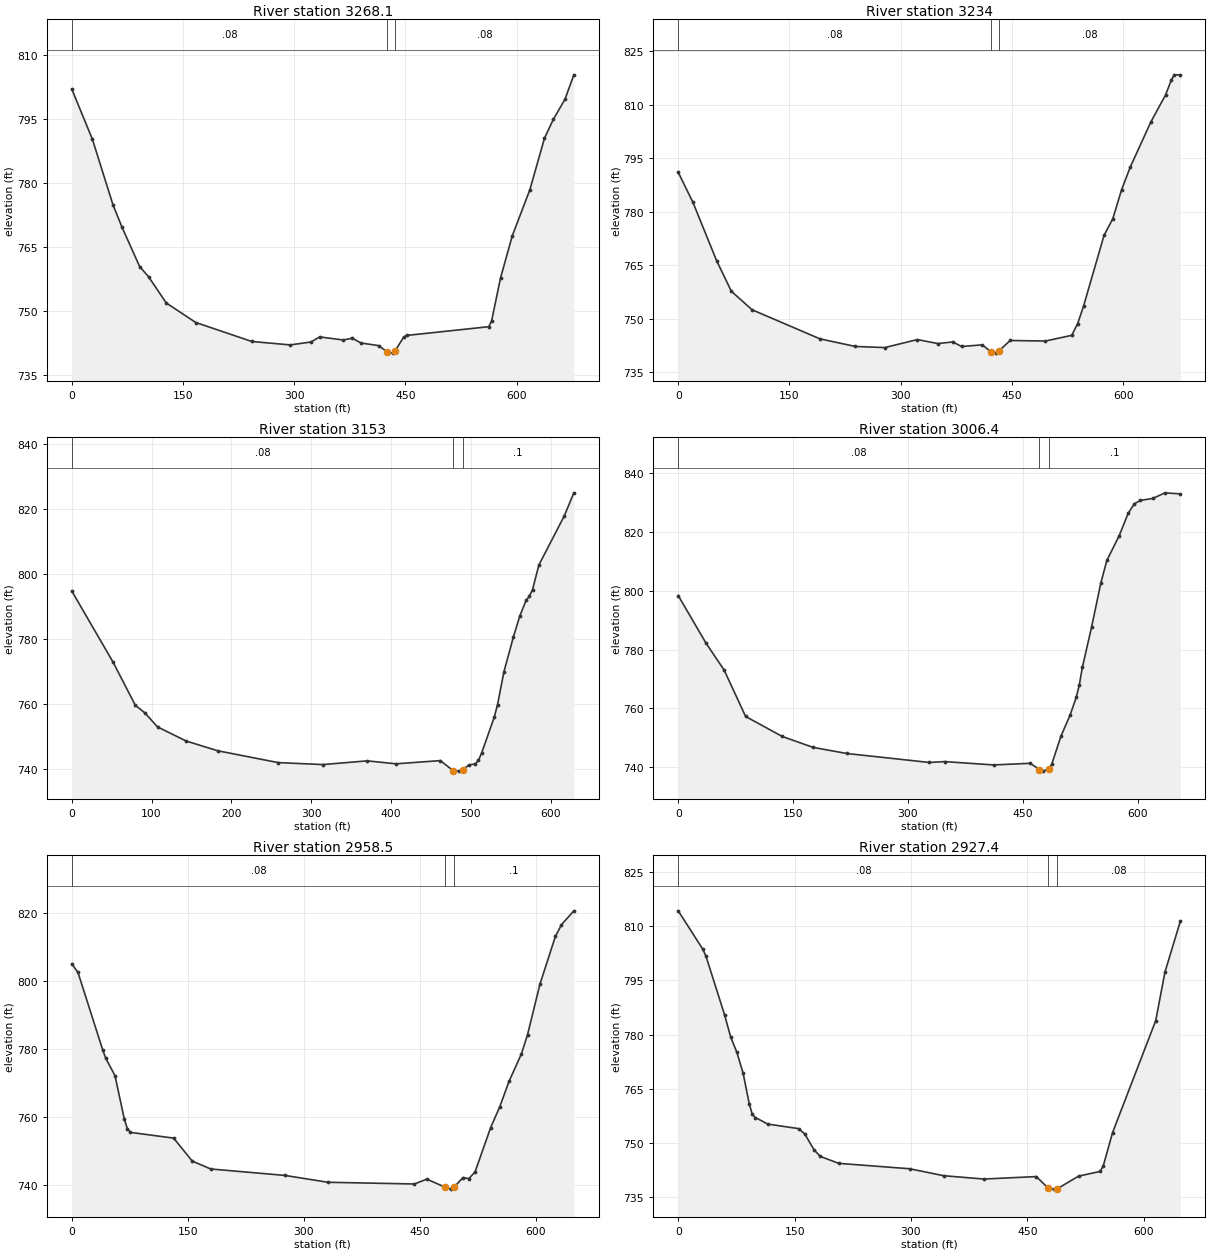
Type RM Length L Ch R = 1 ,3268.1  ,34,34.1,32.2
XS GIS Cut Line= 4
     1717042.645      384111.804     1716987.958      383705.554
     1716958.444      383682.116     1716948.895      383452.949
#Sta/Elev= 30
       0  801.94    27.9  790.17    55.7  774.81    67.7  769.66    91.5  760.46
   103.5  758.08   127.4  751.94   167.2  747.37   242.8  742.93   294.5  742.13
   322.4  742.81   334.3     744   366.1  743.28   378.1   743.7     390  742.58
   413.7  741.97     425  740.55   432.5  740.21   436.3  740.82   447.6  743.97
   451.6  744.35   562.3  746.39   566.2  747.81   578.1  757.74   593.9  767.59
   617.6  778.36   637.4  790.44   649.3  794.85   665.1  799.58     677  805.27
#Mann= 3 , 0 , 0
       0     .08       0     425    .045       0   436.3     .08       0
Bank Sta=425,436.3
XS Rating Curve= 0 ,0
Exp/Cntr=0.3,0.1

Type RM Length L Ch R = 1 ,3234    ,65.3,81,97.8
XS GIS Cut Line= 4
     1717072.159      384097.047     1717017.472      383690.797
     1716987.958      383667.359     1716978.409      383438.192
#Sta/Elev= 30
       0  791.04    19.9  782.58    51.7  766.28    71.6  757.69    99.5   752.5
     191  744.34   238.8   742.2   278.6  741.89   322.4  744.13   350.2  743.01
   370.1  743.47   382.1  742.19   409.9  742.65   421.2  740.78   428.8  740.33
   432.5  740.98   447.6  743.88   495.1  743.72   530.6  745.32   538.6  748.62
   546.5   753.5   574.2  773.38     586  778.05   597.9  786.21   609.7   792.6
   637.4  805.22   657.2  812.79   665.1  817.06   669.1  818.38     677  818.39
#Mann= 3 , 0 , 0
       0     .08       0   421.2    .045       0   432.5     .08       0
Bank Sta=421.2,432.5
XS Rating Curve= 0 ,0
Exp/Cntr=0.3,0.1

Type RM Length L Ch R = 1 ,3153    ,144.1,146.6,151.2
XS GIS Cut Line= 2
     1717102.541       384113.54      1717058.27      383485.935
#Sta/Elev= 30
       0  794.84    51.8  772.91    79.6  759.66    91.6  757.32   107.5  752.99
   143.4  748.64   183.2  745.63   258.8     742   314.6   741.4   370.3  742.54
   406.2  741.63   461.9  742.62   477.8  739.57   485.8  739.38   489.8  739.87
   497.8  741.25   505.7  741.66   509.7  742.68   513.7     745   529.6   756.1
   533.6  759.89   541.6  769.99   553.5  780.72   561.5  787.16   569.4  791.96
   573.4  793.17   577.4  795.24   585.4  802.84   617.2  817.94   629.2  825.05
#Mann= 3 , 0 , 0
       0     .08       0   477.8    .045       0   489.8      .1       0
Bank Sta=477.8,489.8
XS Rating Curve= 0 ,0
Exp/Cntr=0.3,0.1

Type RM Length L Ch R = 1 ,3006.4  ,26.1,47.9,77.8
XS GIS Cut Line= 2
     1717150.284      384131.769     1717228.409      383480.727
#Sta/Elev= 30
       0  798.38      36   782.3      60     773      88  757.22   135.9  750.41
   175.9  746.71   219.9  744.62   327.9  741.56   347.8  741.86   411.8  740.72
   459.8  741.27   471.8  739.11   475.8  738.61   483.8  739.28   487.8  740.98
   499.8  750.49   511.8  757.73   519.8  763.74   523.8     768   527.8  773.96
   539.8  787.64   551.8  802.56   559.8  810.37   575.8  818.73   587.7  826.45
   595.7  829.64   603.7  830.79   619.7  831.46   635.7  833.37   655.7     833
#Mann= 3 , 0 , 0
       0     .08       0   471.8    .045       0   483.8      .1       0
Bank Sta=471.8,483.8
XS Rating Curve= 0 ,0
Exp/Cntr=0.3,0.1

Type RM Length L Ch R = 1 ,2958.5  ,40.4,31.2,30.5
XS GIS Cut Line= 4
     1717241.734      384143.054     1717227.411      383676.029
     1717273.765      383679.675     1717266.691      383544.095
#Sta/Elev= 30
       0  804.98       8   802.5    39.9   779.8    43.9  777.29    55.9  772.17
    67.9  759.47    71.9  756.57    75.9   755.5   131.8  753.81   155.8  747.08
   179.7  744.75   275.6  742.86   331.5  740.84   443.3  740.34   459.3  741.77
   482.7  739.42   490.5  738.83   494.4  739.35     506  742.22   513.7  741.92
   521.7  743.88   541.7   756.8   553.7  763.05   565.6  770.45   581.6  778.51
   589.6   784.2   605.6  798.99   625.6  813.03   633.5   816.5   649.5  820.57
#Mann= 3 , 0 , 0
       0     .08       0   482.7    .045       0   494.4      .1       0
Bank Sta=482.7,494.4
XS Rating Curve= 0 ,0
Exp/Cntr=0.3,0.1

Type RM Length L Ch R = 1 ,2927.4  ,84.8,71.4,40.3
XS GIS Cut Line= 4
     1717251.456      384170.831     1717240.605      383705.337
     1717282.923      383710.762     1717276.413      383571.873
#Sta/Elev= 30
       0  814.25    31.8  803.59    35.8  801.68    59.7  785.51    67.6  779.36
    75.6  775.11    83.6   769.4    91.5  760.95    95.5  757.95    99.5  757.09
   115.4  755.28   155.2  754.02   163.2  752.52   175.1  748.16   183.1  746.34
   206.9  744.42   298.5  742.92   342.2     741     394  740.08   461.6  740.76
   477.3  737.53     485  737.29   488.9  737.42   516.2  740.89     544  742.19
     548  743.73   559.9  752.89   615.6  783.89   627.5  797.31   647.3  811.36
#Mann= 3 , 0 , 0
       0     .08       0   477.3    .045       0   488.9     .08       0
Bank Sta=477.3,488.9
XS Rating Curve= 0 ,0
Exp/Cntr=0.3,0.1

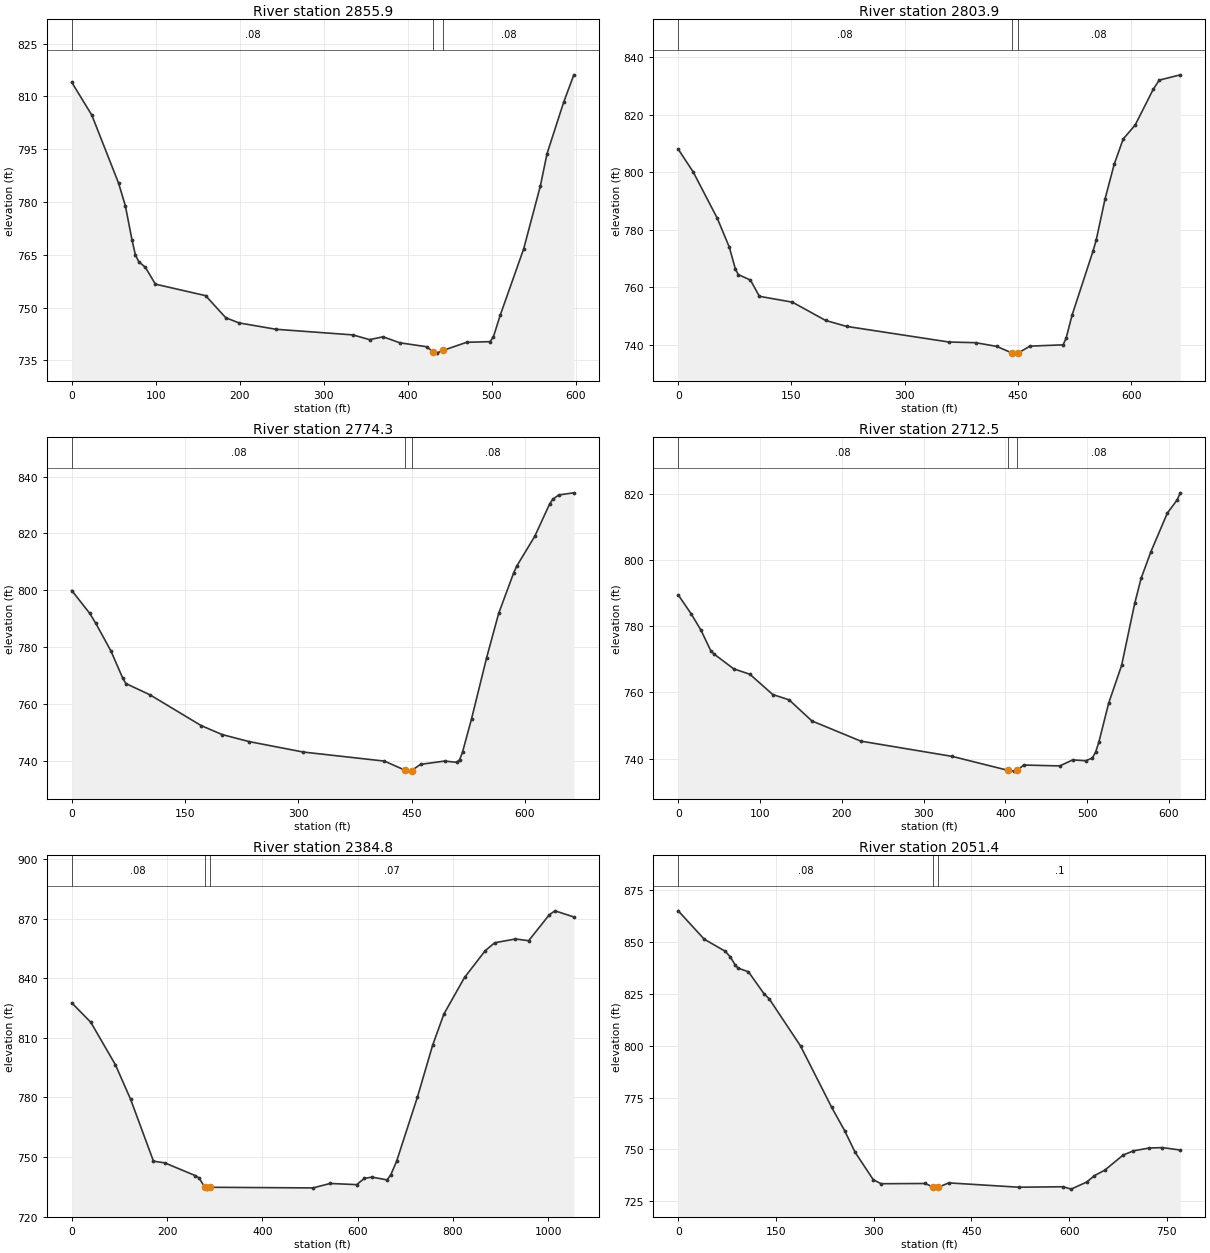
Type RM Length L Ch R = 1 ,2855.9  ,51.9,52,52.4
XS GIS Cut Line= 2
     1717296.986      384176.908     1717324.763      383579.685
#Sta/Elev= 30
       0  814.01    23.9  804.68    55.8  785.32    63.8  778.94    71.7  769.26
    75.7  765.06    79.7  763.06    87.7  761.42    99.6  756.66   159.4  753.39
   183.4  747.11   199.3  745.64   243.1  743.84   334.8  742.24   354.7  740.89
   370.7   741.7   390.6     740   422.5  738.88   430.5  737.39   434.4  737.06
   442.4  737.85   470.3  740.14   498.2  740.32   502.2  741.76   510.2  747.82
   538.1  766.65     558  784.53     566  793.76   585.9  808.44   597.9  816.14
#Mann= 3 , 0 , 0
       0     .08       0   430.5    .045       0   442.4     .08       0
Bank Sta=430.5,442.4
XS Rating Curve= 0 ,0
Exp/Cntr=0.3,0.1

Type RM Length L Ch R = 1 ,2803.9  ,29.6,29.6,29.6
XS GIS Cut Line= 2
     1717345.597       384189.06     1717380.319      383524.998
#Sta/Elev= 30
       0  808.01    19.9  800.08    51.8  783.98    67.7  773.97    75.7   766.4
    79.6  764.47    95.6  762.59   107.5  756.94   151.3   754.9   195.1  748.57
     223  746.49   358.4  741.07   394.2  740.83   422.1  739.53     442  737.26
     446  737.21     450  737.22   465.9  739.64   509.7  740.09   513.7  742.34
   521.6  750.37   549.5  772.73   553.5  776.35   565.4  790.85   577.4  802.76
   589.3  811.54   605.2  816.41   629.1   828.8   637.1     832     665  833.84
#Mann= 3 , 0 , 0
       0     .08       0     442    .045       0     450     .08       0
Bank Sta=442,450
XS Rating Curve= 0 ,0
Exp/Cntr=0.3,0.1

Type RM Length L Ch R = 1 ,2774.3  ,63.6,61.9,63.1
XS GIS Cut Line= 2
     1717375.111      384190.797     1717409.833      383526.734
#Sta/Elev= 30
       0  799.88    23.9   791.8    31.8  788.34    51.8  778.63    67.7  768.92
    71.7  767.13   103.5  763.18   171.2  752.36   199.1  749.18   234.9   746.7
   306.6  743.02   414.1  739.83     442  736.56     446   736.3     450  736.48
   461.9  738.68   493.8  739.84   509.7   739.4   513.7  740.33   517.6  743.04
   529.6  754.81   549.5  776.25   565.4   791.8   585.3  806.09   589.3  808.46
   613.2  818.95   633.1  830.45   637.1  832.02   645.1  833.53     665  834.27
#Mann= 3 , 0 , 0
       0     .08       0     442    .045       0     450     .08       0
Bank Sta=442,450
XS Rating Curve= 0 ,0
Exp/Cntr=0.3,0.1

Type RM Length L Ch R = 1 ,2712.5  ,319.4,327.6,332.6
XS GIS Cut Line= 2
     1717391.604      384174.304     1717486.222      383567.533
#Sta/Elev= 30
       0  789.43      16  783.65    27.9  778.74    39.9  772.54    43.9  771.57
    67.8  767.13    87.7  765.48   115.6  759.38   135.6  757.77   163.5  751.41
   223.3  745.32     335  740.72   402.8  736.54   410.7  736.27   414.7  736.58
   422.7  738.11   466.6  737.84   482.5  739.65   498.5  739.41   506.4  740.21
   510.4  741.95   514.4  744.93   526.4  756.72   542.3  768.17   558.3  786.85
   566.2  794.46   578.2   802.5   598.2  814.09   610.1  818.04   614.1  820.22
#Mann= 3 , 0 , 0
       0     .08       0   402.8    .045       0   414.7     .08       0
Bank Sta=402.8,414.7
XS Rating Curve= 0 ,0
Exp/Cntr=0.3,0.1

Type RM Length L Ch R = 1 ,2384.8  ,322.2,333.4,344.4
XS GIS Cut Line= 3
     1717596.465      384255.033     1717815.822      383550.736
     1717673.895      383268.184
#Sta/Elev= 30
       0  827.52    39.9  817.79    91.7  796.36   123.6  778.95   171.5  747.86
   195.4  746.99   259.2  740.61   267.2   739.4   279.1   734.8   283.1  733.79
   291.1  734.72   506.4   734.4   542.3  736.64   598.1  736.05   614.1  739.17
     630  739.85   661.9  738.44   669.9  741.12   681.8  747.78   725.7  780.23
   757.4  806.16   781.1  821.92   824.6  840.38   868.1  853.87   887.9   857.8
   931.3   859.7     959  858.83  1002.5  871.92  1014.3  873.87  1053.9  870.78
#Mann= 3 , 0 , 0
       0     .08       0   279.1    .045       0   291.1     .07       0
Bank Sta=279.1,291.1
XS Rating Curve= 0 ,0
Exp/Cntr=0.3,0.1

Type RM Length L Ch R = 1 ,2051.4  ,330.4,335.7,340.6
XS GIS Cut Line= 2
     1717718.638       384369.17      1718224.28      383787.573
#Sta/Elev= 30
       0  865.14    39.9  851.45    71.9  845.68    79.9  842.95    87.8   838.8
    91.8  837.51   107.8  835.71   131.8  825.08   139.8  822.61   187.7  799.94
   235.6  770.28   255.6  758.95   271.5  748.64   299.5  735.34   311.5  733.45
   379.3  733.56   391.3   731.8   399.3  731.75   415.3  733.85   523.1  731.76
     591  731.99     603  730.84   626.9  734.24   638.9  737.34   654.9  740.03
   682.8  747.25   698.8  749.33   722.8  750.66   742.7  750.88   770.7  749.71
#Mann= 3 , 0 , 0
       0     .08       0   391.3    .045       0   399.3      .1       0
Bank Sta=391.3,399.3
XS Rating Curve= 0 ,0
Exp/Cntr=0.3,0.1

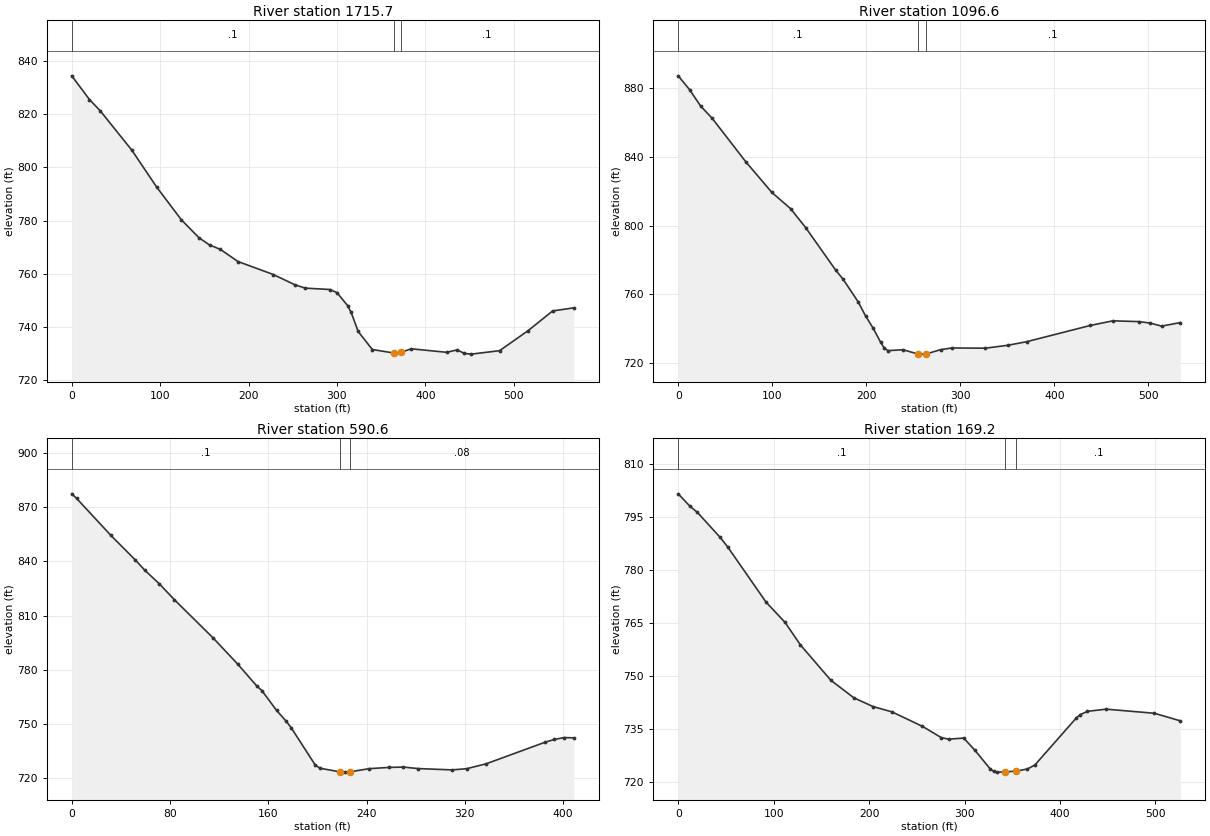
Type RM Length L Ch R = 1 ,1715.7  ,599,619.1,607.7
XS GIS Cut Line= 2
     1717885.267      384542.489     1718334.957      384195.559
#Sta/Elev= 30
       0  834.46      20  825.55      32  821.38      68  806.47      96  792.63
     124  780.29     144  773.52     156   770.8     168  769.19     188  764.61
     228  759.72     252  755.92     264   754.6     292  754.08     300  752.91
     312  748.06     316  745.52     324  738.29     340  731.51     364   730.2
     372  730.39     384  731.77     424  730.46     436  731.36     444  730.05
     452  729.77     484  731.07     516  738.53     544  746.02     568  747.18
#Mann= 3 , 0 , 0
       0      .1       0     364    .045       0     372      .1       0
Bank Sta=364,372
XS Rating Curve= 0 ,0
Exp/Cntr=0.3,0.1

Type RM Length L Ch R = 1 ,1096.6  ,506.1,506,475.5
XS GIS Cut Line= 2
      1718061.52       384810.75     1718554.576      384605.889
#Sta/Elev= 30
       0  887.14      12  879.12    23.9  869.48    35.9  862.55    71.7   837.2
    99.6  819.23   119.5   809.8   135.5  798.78   167.4  774.06   175.3  768.73
   191.3   755.6   199.2  747.34   207.2  740.29   215.2  732.05   219.2  728.57
   223.1  727.15   239.1  727.69     255  725.16     263  725.12   278.9   727.7
   290.9   728.7   326.7  728.58   350.6  730.28   370.6  732.37   438.3  741.82
   462.2  744.51   490.1  744.04     502  743.18     514  741.42   533.9  743.48
#Mann= 3 , 0 , 0
       0      .1       0     255    .045       0     263      .1       0
Bank Sta=255,263
XS Rating Curve= 0 ,0
Exp/Cntr=0.3,0.1

Type RM Length L Ch R = 1 ,590.6   ,458.1,421.4,384.1
XS GIS Cut Line= 2
     1718308.048      385163.181     1718650.062      384939.223
#Sta/Elev= 30
       0  877.53       4  874.95    31.8   854.5    51.6  840.92    59.5  835.11
    71.4  827.53    83.4  818.88   115.1  797.55     135  783.14   150.8  770.76
   154.8  768.35   166.7   757.4   174.6  751.31   178.6  747.79   198.4  726.88
   202.4  725.22   218.3  723.25   222.3   723.1   226.2  723.22   242.1  725.02
     258  725.71   269.9  725.91   281.8  725.08   309.6  724.34   321.5     725
   337.4  727.72     385   739.6   392.9  741.23   400.9  742.28   408.8  742.12
#Mann= 3 , 0 , 0
       0      .1       0   218.3    .045       0   226.2     .08       0
Bank Sta=218.3,226.2
XS Rating Curve= 0 ,0
Exp/Cntr=0.3,0.1

Type RM Length L Ch R = 1 ,169.2   ,179.3,169.2,159.1
XS GIS Cut Line= 4
      1718842.77      385567.695     1718853.187      385315.959
     1718768.117      385147.556     1718776.798      385062.486
#Sta/Elev= 30
       0  801.56      12  798.12      20  796.32      44  789.22      52  786.45
      92   770.9     112  765.13     128  758.79     160  748.74     184   743.8
     204  741.33     224  739.81   255.9  735.71   275.5  732.55   283.4  732.08
   299.1   732.4   310.9  728.93   326.6  723.75   330.6  722.93   334.5  722.75
   342.4  722.83   354.2  723.04   365.9  723.64   373.8  724.79     417  738.06
     421  738.98   428.8  739.97   448.4  740.58   498.9  739.42   526.1  737.27
#Mann= 3 , 0 , 0
       0      .1       0   342.4    .045       0   354.2      .1       0
Bank Sta=342.4,354.2
XS Rating Curve= 0 ,0
Exp/Cntr=0.3,0.1

Chan Stop Cuts=-1
Use User Specified Reach Order=0
Composite Channel Slope=5